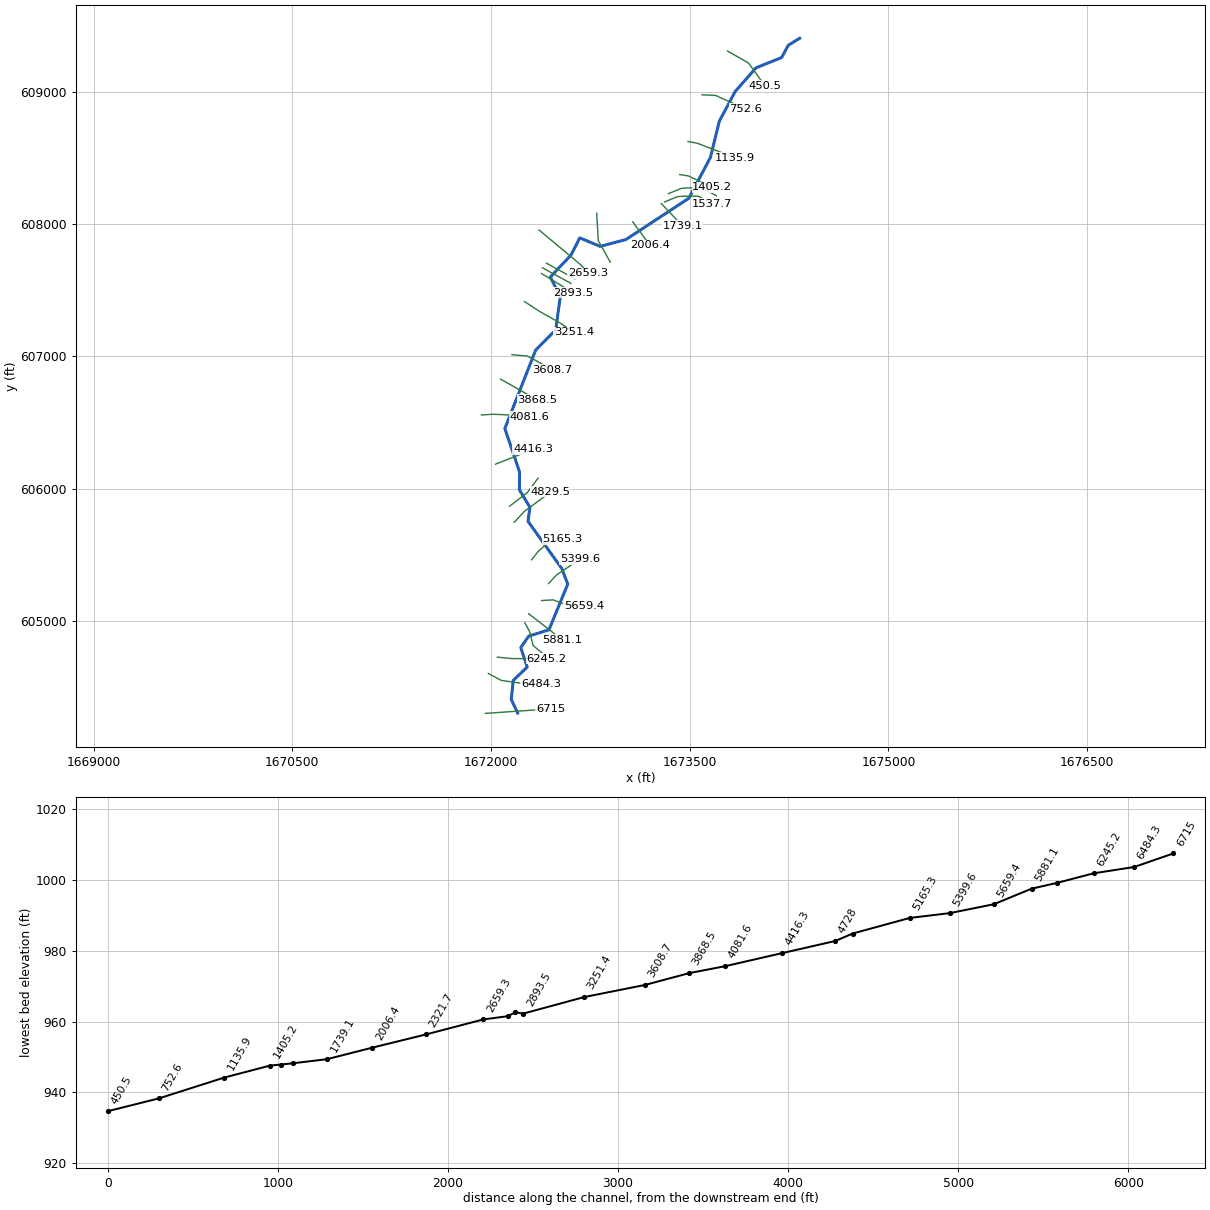
--- LNGSRN.prj (project) ---

Proj Title=LNGSRN
Current Plan=p01
Default Exp/Contr=0,0
English Units
Geom File=g01
Flow File=f01
Plan File=p01
BEGIN DESCRIPTION:
END DESCRIPTION:
DSS Export Rating Curves= 0
DSS Export Rating Curve Sorted= 0
DSS Export Volume Flow Curves= 0
DXF OffsetX= 0
DXF OffsetY= 0
DXF ScaleX= 0
DXF ScaleY= 0

--- LNGSRN.p01 (plan) ---

Plan Title=Floodplain
Program Version=4.00
Geom File=g01
Flow File=f01
K Sum by GR=0
Std Step Tol=0.01
Critical Tol=0.01
Num of Std Step Trials=20
Max Error Tol=0.3
Flow Tol Ratio=0.001
Split Flow NTrial=30
Split Flow Tol=0.02
Split Flow Ratio=0.02
Log Output Level=0
Friction Slope Method=1
Unsteady Friction Slope Method=2
Unsteady Bridges Friction Slope Method=1
Global Log Level=0
CheckData=False
Run HTab=0
Run UNet=0
Run PostProcess=0
UNET Theta=0
UNET Theta Warmup=0
UNET ZTol=0
UNET ZSATol=0
UNET MxIter=0
UNET MaxInSteps=0
UNET DtIC=0
UNET DtMin=0
UNET MaxCRTS=0
UNET WFStab=0
UNET SFStab=0
UNET WFX=0
UNET SFX=0
UNET DSS MLevel=0
UNET DZMax Abort=0
UNET Convert EG Bridges=0
UNET Use Existing IB Tables=0
UNET Froude Limit=0
UNET Froude Power=0
Write IC File=0
Echo Input=False
Echo Output=False
Write Detailed=0

--- LNGSRN.f01 (steady flow) ---

Flow Title=NFF Regression Equation
Program Version=4.10
Number of Profiles= 1
Profile Names=P100yr
River Rch & RM=LNGSRN,Main            ,6715
915.4967
River Rch & RM=LNGSRN,Main            ,5881.1
924.5028
River Rch & RM=LNGSRN,Main            ,3608.7
1018.315
River Rch & RM=LNGSRN,Main            ,2893.5
1111.201
River Rch & RM=LNGSRN,Main            ,2321.7
1279.053
River Rch & RM=LNGSRN,Main            ,1135.9
1347.634
Boundary for River Rch & Prof#=LNGSRN,Main            , 1
Up Type= 0
Dn Type= 1
Dn Known WS=939.64
DSS Import GetInterval= 0
DSS Import GetPeak= 0
DSS Import FillOption= 0

--- LNGSRN.g01 (geometry) ---

Geom Title=USGS 10m DEM
Program Version=4.10

River Reach=LNGSRN          ,Main
Reach XY= 30
     1672201.218      604308.671     1672153.041      604410.494
     1672167.257      604554.128     1672273.166      604656.081
     1672224.577      604802.913     1672284.603      604889.487
     1672437.164      604936.579     1672579.453      605282.022
     1672533.518      605400.555     1672279.268      605755.665
     1672293.718      605861.275     1672214.372      605994.039
     1672215.119      606129.059     1672104.529      606456.355
     1672337.237      607048.774     1672488.205      607200.038
     1672522.717      607450.793     1672447.502      607599.687
     1672603.503      607765.114     1672670.008      607895.057
     1672823.932      607831.001     1673018.294      607882.853
     1673493.193      608194.225     1673655.866      608502.052
     1673723.466      608776.379     1673842.607      608999.686
     1674000.176      609178.636     1674194.082      609256.588
     1674243.023      609348.558     1674329.395      609401.292

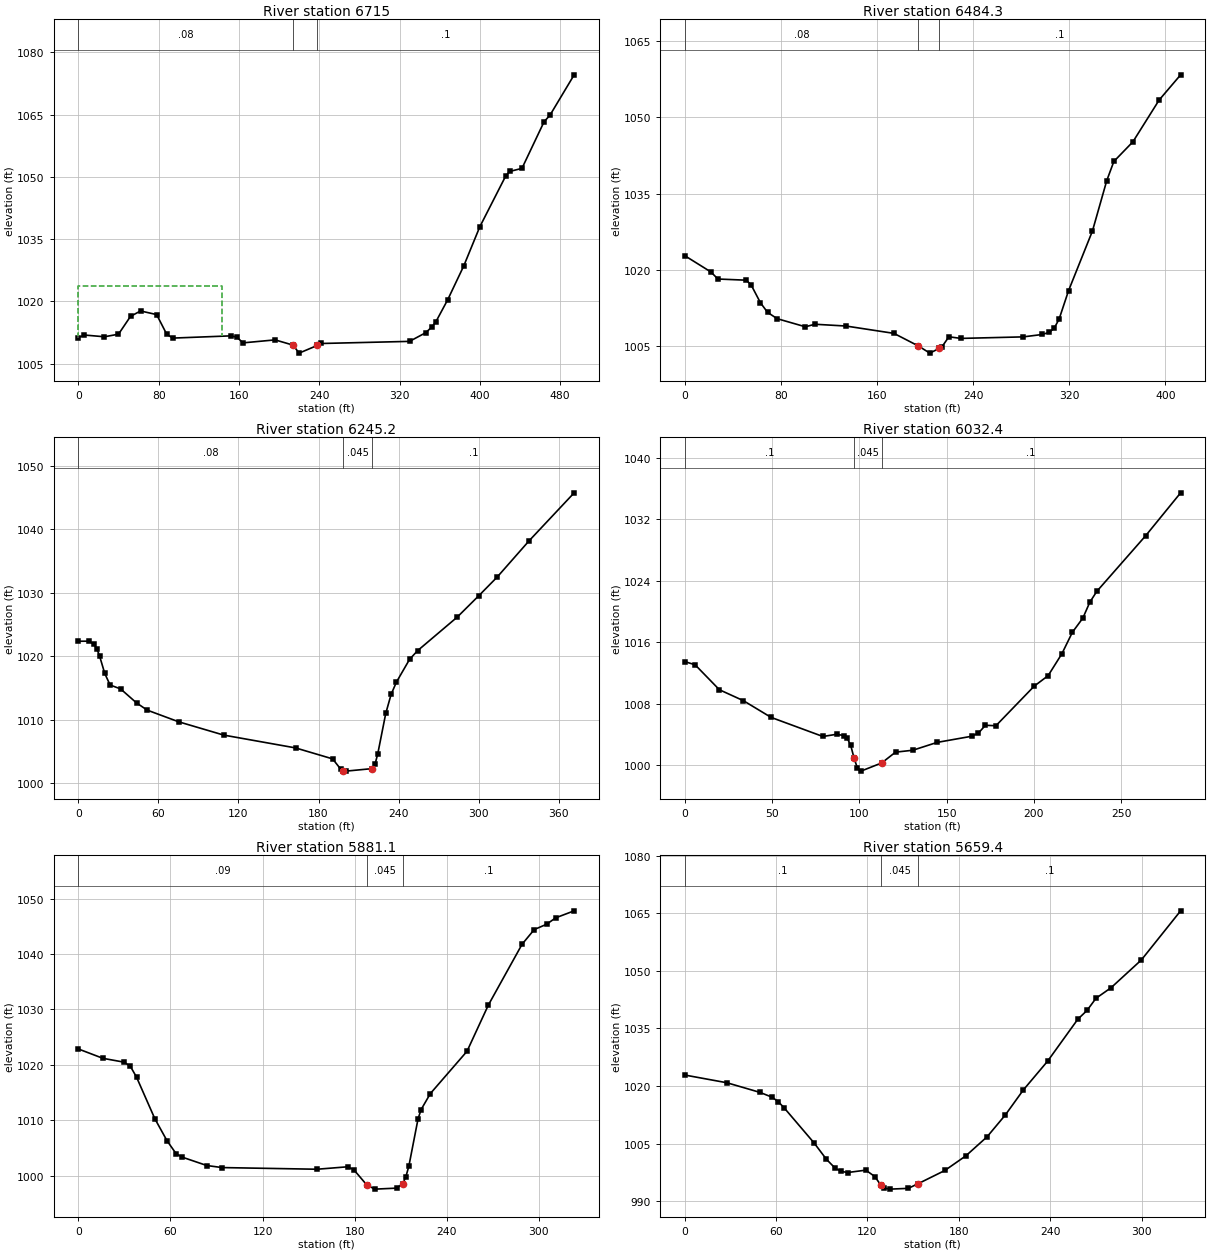
Type RM Length L Ch R = 1 ,6715    ,232.8,230.8,229.1
XS GIS Cut Line= 2
     1671957.671      604306.204     1672450.379      604339.971
#Sta/Elev= 30
       0 1011.26       6 1011.89      26 1011.47      40 1012.09      52 1016.39
      62 1017.69      78 1016.81      88  1012.1      94 1011.15     152 1011.69
     158 1011.37     164    1010     196 1010.72   213.9 1009.46   219.9 1007.53
     238 1009.38   241.9 1009.85   329.9 1010.36   345.9 1012.43   351.9 1013.77
   355.9 1014.97   367.9 1020.37   383.9 1028.52   399.9 1037.95   425.9 1050.28
   429.9  1051.3   441.9 1052.03   463.9 1063.24   469.9 1064.87   493.9 1074.56
#Mann= 3 , 0 , 0
       0     .08       0   213.9    .045       0     238      .1       0
#XS Ineff= 2 , 0
          143.49 1023.67
Permanent Ineff=
       F       F
Bank Sta=213.9,238
XS Rating Curve= 0 ,0
Exp/Cntr=0.3,0.1

Type RM Length L Ch R = 1 ,6484.3  ,238.7,239,240.3
XS GIS Cut Line= 4
     1671979.893      604607.332     1672077.115      604555.249
      1672280.24      604525.735     1672377.462      604527.471
#Sta/Elev= 30
       0 1022.82    21.7 1019.63    27.6 1018.24    51.2 1018.01    55.2 1017.09
      63 1013.57    68.9  1011.7    76.8 1010.46   100.4 1008.86   108.3 1009.36
   134.2 1009.01   174.1 1007.57   194.5 1005.09     204 1003.69   211.9 1004.63
   213.9 1004.87   219.9  1006.9   229.9 1006.58   281.7 1006.88   297.6 1007.35
   303.6 1007.79   307.6 1008.62   311.6 1010.35   319.5 1015.96   339.4 1027.68
   351.3 1037.56   357.2 1041.32   373.1 1045.19   394.9 1053.38   412.8 1058.33
#Mann= 3 , 0 , 0
       0     .08       0   194.5    .045       0   211.9      .1       0
Bank Sta=194.5,211.9
XS Rating Curve= 0 ,0
Exp/Cntr=0.3,0.1

Type RM Length L Ch R = 1 ,6245.2  ,238,212.8,182.9
XS GIS Cut Line= 3
     1672047.977      604730.712     1672156.484      604719.861
     1672419.071      604717.691
#Sta/Elev= 30
       0 1022.38     7.9 1022.39    11.9 1021.87    13.9 1021.16    15.9 1020.07
    19.8  1017.3    23.8 1015.48    31.7 1014.86    43.6 1012.66    51.6 1011.52
    75.3 1009.67     109 1007.58   162.8 1005.56   190.6 1003.83   196.6 1002.22
   198.6 1001.96   200.6  1001.9   220.4  1002.3   222.4 1003.02   224.4 1004.62
   230.4    1011   234.4 1013.99   238.4 1015.94   248.3 1019.54   254.3  1020.9
   284.1 1026.21     300 1029.53     314 1032.52   337.8 1038.21   371.6 1045.78
#Mann= 3 , 0 , 0
       0     .08       0   198.6    .045       0   220.4      .1       0
Bank Sta=198.6,220.4
XS Rating Curve= 0 ,0
Exp/Cntr=0.3,0.1

Type RM Length L Ch R = 1 ,6032.4  ,136.2,151.3,166.2
XS GIS Cut Line= 4
     1672255.848      604989.798     1672291.004      604923.391
     1672318.348      604817.923     1672395.171      604754.121
#Sta/Elev= 30
       0 1013.48     5.9 1013.07    19.8 1009.82    33.6 1008.39    49.4 1006.22
    79.1 1003.73      87 1004.02      91 1003.85      93 1003.52      95  1002.6
      97 1000.88    98.9   999.6   100.9  999.22   112.8 1000.29   120.7 1001.69
   130.6 1001.94   144.5 1002.96   164.3 1003.76   168.2 1004.18   172.2 1005.19
   178.2 1005.13   200.1 1010.28   208.1 1011.65     216 1014.51     222  1017.3
     228 1019.15     232 1021.22     236 1022.63     264 1029.88     284 1035.46
#Mann= 3 , 0 , 0
       0      .1       0      97    .045       0   112.8      .1       0
Bank Sta=97,112.8
XS Rating Curve= 0 ,0
Exp/Cntr=0.3,0.1

Type RM Length L Ch R = 1 ,5881.1  ,214.2,221.7,228.5
XS GIS Cut Line= 2
     1672283.712      605058.721     1672538.921      604860.805
#Sta/Elev= 30
       0 1022.86      16 1021.17    29.9 1020.47    33.9 1019.72    37.9 1017.78
    49.8 1010.29    57.8 1006.28    63.8 1003.92    67.8 1003.32    83.7 1001.82
    93.7 1001.45   155.5 1001.15   175.4 1001.59   179.4 1001.08   188.2  998.22
   193.4  997.56   207.3  997.74   211.3  998.52   213.3  999.74   215.3 1001.69
   221.3 1010.24   223.3 1011.92   229.3  1014.8   253.2 1022.44   267.1 1030.78
   289.1 1041.77     297 1044.41     305 1045.36     311 1046.53     323 1047.79
#Mann= 3 , 0 , 0
       0     .09       0   188.2    .045       0   211.3      .1       0
Bank Sta=188.2,211.3
XS Rating Curve= 0 ,0
Exp/Cntr=0.3,0.1

Type RM Length L Ch R = 1 ,5659.4  ,238.2,259.8,280.9
XS GIS Cut Line= 4
     1672380.934       605157.68      1672467.74      605162.888
     1672559.754      605129.902     1672700.379      605119.485
#Sta/Elev= 30
       0 1022.87    27.7 1020.86    49.4 1018.35    57.3 1017.11    61.3 1015.97
    65.2 1014.36      85 1005.16      93 1000.95    98.9  998.57   102.9  997.79
   106.9  997.49   118.9  998.11   124.9  996.42   128.8  994.18   130.8  993.44
   134.8  993.17   146.8  993.37   153.5  994.63   170.8  998.02   184.7 1001.86
   198.6 1006.81   210.5 1012.45   222.4    1019   238.3 1026.47   258.2 1037.42
   264.2 1039.68   270.1 1042.85     280  1045.6   299.9 1052.83   325.7 1065.62
#Mann= 3 , 0 , 0
       0      .1       0   128.8    .045       0   153.5      .1       0
Bank Sta=128.8,153.5
XS Rating Curve= 0 ,0
Exp/Cntr=0.3,0.1

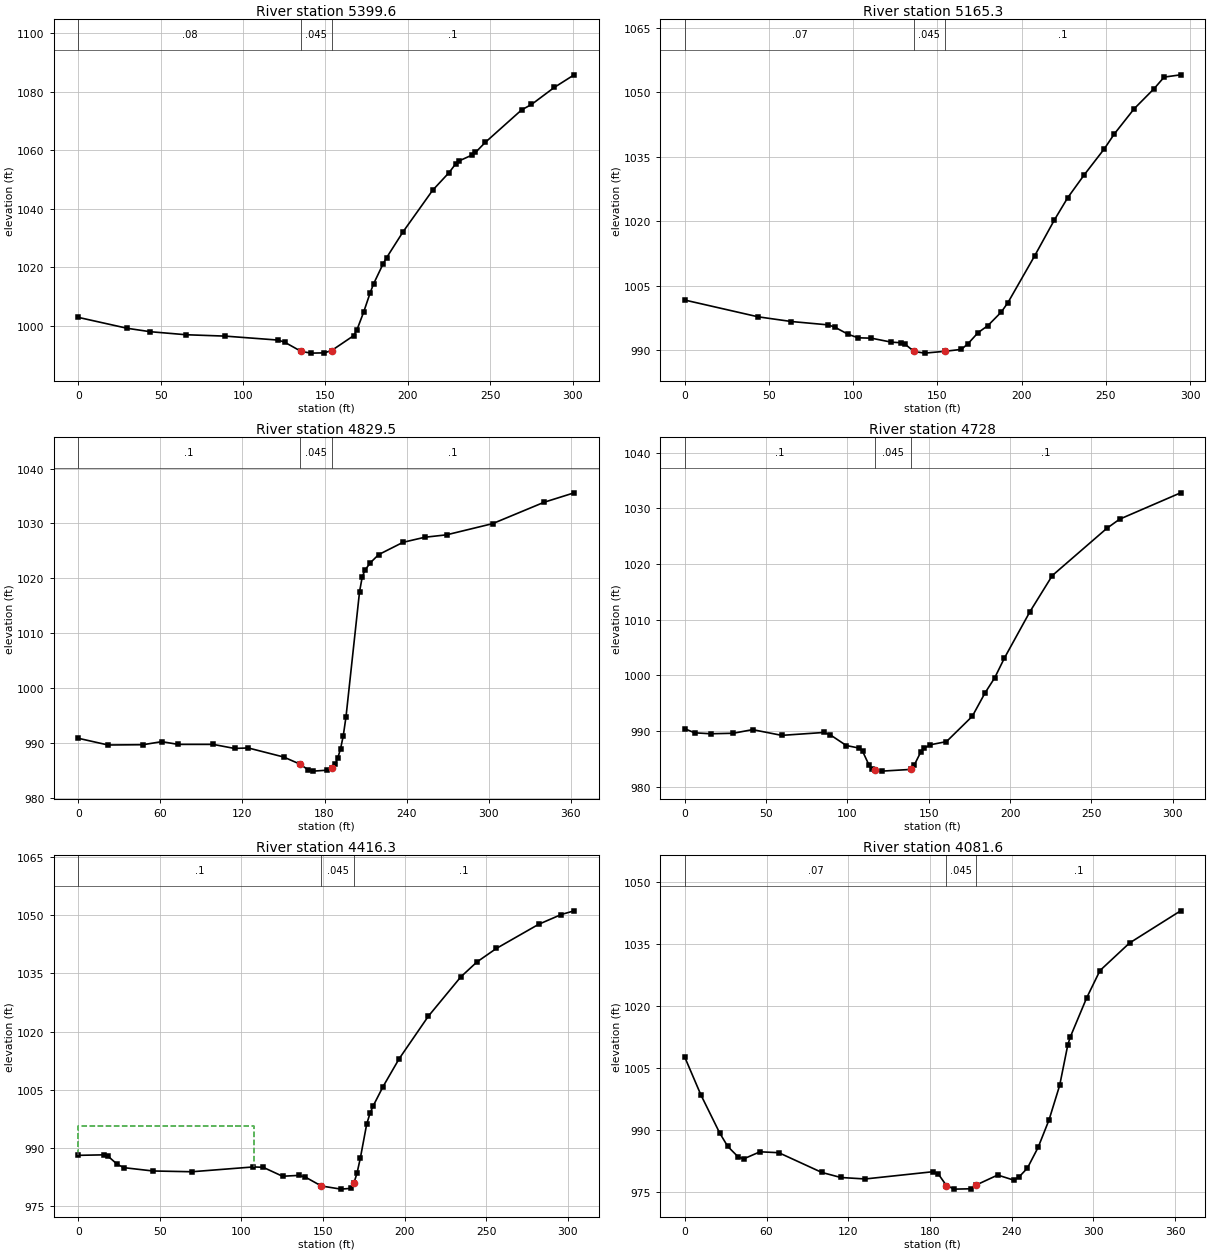
Type RM Length L Ch R = 1 ,5399.6  ,230.9,234.3,236.8
XS GIS Cut Line= 3
     1672434.754      605286.152     1672493.782      605350.388
     1672670.865       605470.18
#Sta/Elev= 30
       0 1002.86    29.7  999.13    43.6  997.97    65.4  996.93    89.2  996.46
   121.2  995.11   125.2   994.4   135.2  991.26   141.2  990.65   149.2  990.74
   153.7  991.51   167.2  996.64   169.2   998.7   173.2 1004.65   177.2 1011.31
   179.2 1014.27   185.1 1021.25   187.1 1023.22   197.1 1032.07   215.1 1046.29
   225.1 1052.34   229.1 1055.32   231.1  1056.3   239.1 1058.33   241.1  1059.2
   247.1 1062.67   269.1 1073.73   275.1 1075.58     289 1081.43     301 1085.71
#Mann= 3 , 0 , 0
       0     .08       0   135.2    .045       0   153.7      .1       0
Bank Sta=135.2,153.7
XS Rating Curve= 0 ,0
Exp/Cntr=0.3,0.1

Type RM Length L Ch R = 1 ,5165.3  ,332.1,335.8,333
XS GIS Cut Line= 4
     1672306.282      605464.971     1672354.893      605527.471
     1672438.226      605600.388     1672540.657      605621.221
#Sta/Elev= 30
       0 1001.66    43.6  997.75    63.3  996.66    85.1  995.88    89.1  995.34
      97  993.68   102.9  992.87   110.8  992.78   122.7  991.85   128.6  991.72
   130.6  991.44   136.1  989.69   142.4   989.3   154.3  989.72   164.2  990.17
   168.2  991.51   174.1  994.06     180  995.72   187.9  998.86   191.9 1001.09
   207.7 1011.93   219.5 1020.35   227.4 1025.52   237.2 1030.84   249.1 1036.88
     255 1040.33   266.8  1046.2   278.7 1050.91   284.6 1053.58   294.4 1054.11
#Mann= 3 , 0 , 0
       0     .07       0   136.1    .045       0   154.3      .1       0
Bank Sta=136.1,154.3
XS Rating Curve= 0 ,0
Exp/Cntr=0.3,0.1

Type RM Length L Ch R = 1 ,4829.5  ,105.7,101.6,101.6
XS GIS Cut Line= 3
     1672174.337      605747.957     1672252.462      605831.291
     1672452.115       605978.86
#Sta/Elev= 30
       0  990.87    21.7  989.65    47.3   989.7      61  990.26    72.9  989.76
    98.5  989.76   114.2  989.02   124.2  989.11     150  987.47   161.9  986.18
   167.8  985.17   171.8  984.89   181.8  985.06   185.7  985.48   187.7   986.1
   189.7  987.32   191.7  988.94   193.7  991.34   195.7  994.79   205.6 1017.58
   207.6 1020.29   209.6  1021.5   213.5 1022.84   219.5 1024.31   237.4 1026.56
   253.3 1027.48   269.2 1027.92   302.9 1029.96   340.6 1033.86   362.5 1035.57
#Mann= 3 , 0 , 0
       0      .1       0   161.9    .045       0   185.7      .1       0
Bank Sta=161.9,185.7
XS Rating Curve= 0 ,0
Exp/Cntr=0.3,0.1

Type RM Length L Ch R = 1 ,4728    ,317.7,311.6,305
XS GIS Cut Line= 3
     1672139.615      605869.485     1672275.032      605973.652
     1672354.893      606081.291
#Sta/Elev= 30
       0   990.4       6  989.67    15.9   989.5    29.8  989.59    41.7  990.24
    59.6  989.21    85.4  989.73    89.4  989.32    99.3  987.39   107.3  986.92
   109.3  986.38   113.2  983.92   115.2  983.12   117.2  982.97   121.2  982.79
   139.1   983.1     141  983.82     145  986.16     147  986.87     151  987.52
   160.9  988.09   176.8  992.64   184.6  996.82   190.6  999.56   196.5 1003.07
   212.2  1011.4     226 1017.91   259.5 1026.38   267.4 1028.03   304.9 1032.76
#Mann= 3 , 0 , 0
       0      .1       0   117.2    .045       0   139.1      .1       0
Bank Sta=117.2,139.1
XS Rating Curve= 0 ,0
Exp/Cntr=0.3,0.1

Type RM Length L Ch R = 1 ,4416.3  ,342,334.7,325.8
XS GIS Cut Line= 2
     1672033.712      606187.193     1672316.698      606298.305
#Sta/Elev= 30
       0  988.08    15.9  988.21    17.9  987.96    23.8   985.8    27.8  984.91
    45.7  984.05    69.6  983.85   107.3  985.09   113.3     985   125.2  982.69
   135.1  982.91   139.1  982.49     149  980.18     161  979.37   166.9  979.56
   168.9  980.83   170.9  983.55   172.9  987.36   176.8  996.12   178.8  998.88
   180.8 1000.84   186.8 1005.78   196.7 1012.98   214.6 1023.94   234.5 1034.08
   244.4 1037.93   256.3 1041.41   282.2 1047.63   296.1 1050.16     304 1051.11
#Mann= 3 , 0 , 0
       0      .1       0     149    .045       0   168.9      .1       0
#XS Ineff= 2 , 0
          107.88   995.6
Permanent Ineff=
       F       F
Bank Sta=149,168.9
XS Rating Curve= 0 ,0
Exp/Cntr=0.3,0.1

Type RM Length L Ch R = 1 ,4081.6  ,225.4,213.1,201.2
XS GIS Cut Line= 4
     1671927.809      606558.721     1672016.351       606563.93
     1672183.018      606556.985     1672290.657      606543.096
#Sta/Elev= 30
       0 1007.62    11.8  998.51    25.6  989.28    31.5  986.03    39.4  983.41
    43.4  983.03    55.2  984.72      69   984.5   100.6  979.72   114.5   978.5
   132.4  978.14     182  979.89     186  979.39   192.1  976.53   197.9  975.68
   209.8  975.76   213.8  976.66   229.7  979.09   241.6  977.85   245.6  978.71
   251.5  980.76   259.4   985.8   267.4  992.45   275.2  1000.8   281.2 1010.66
   283.1  1012.6     295 1021.98   304.8 1028.61   326.5 1035.28     364 1043.07
#Mann= 3 , 0 , 0
       0     .07       0   192.1    .045       0   213.8      .1       0
Bank Sta=192.1,213.8
XS Rating Curve= 0 ,0
Exp/Cntr=0.3,0.1

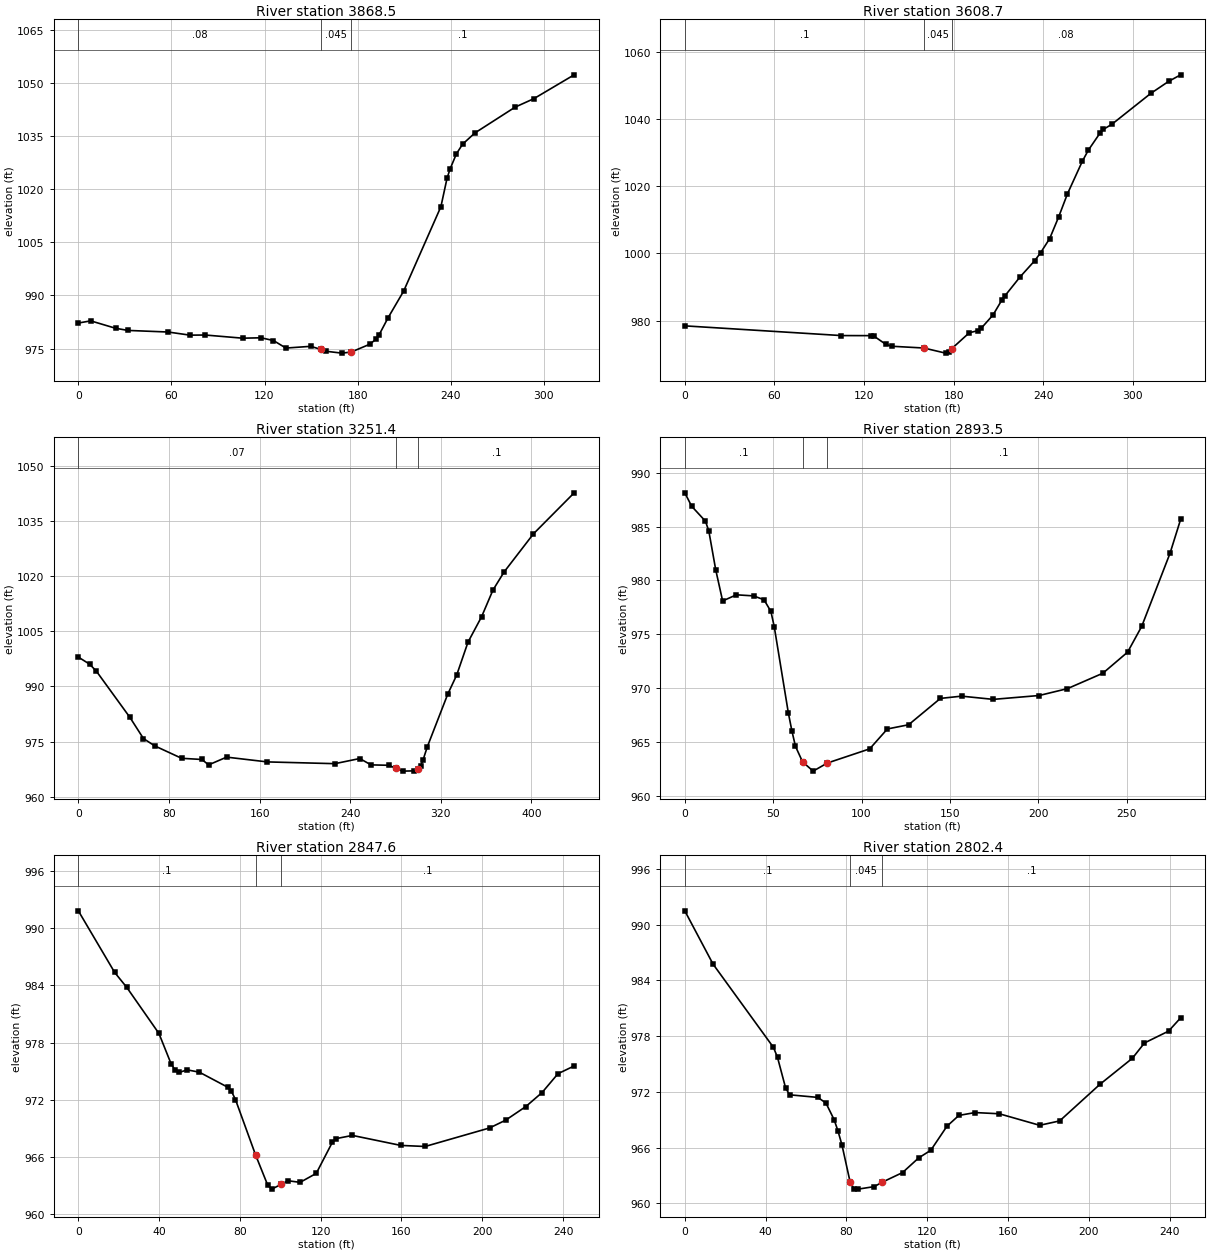
Type RM Length L Ch R = 1 ,3868.5  ,258.4,259.8,259.1
XS GIS Cut Line= 2
     1672071.907      606829.555     1672349.684      606671.568
#Sta/Elev= 30
       0   982.2       8  982.81      24  980.72      32  980.11    57.9  979.66
    71.9  978.78    81.9  978.81   105.9  977.92   117.8  978.03   125.8  977.25
   133.8  975.13   149.8  975.62   156.4  974.74   159.8  974.22   169.8   973.7
   175.8  973.99   187.7  976.18   191.7  977.56   193.7  978.73   199.7  983.72
   209.7  991.22   233.7 1015.05   237.7 1023.15   239.7 1025.78   243.7 1029.98
   247.7 1032.71   255.6 1035.87   281.6 1043.18   293.6 1045.55   319.6 1052.29
#Mann= 3 , 0 , 0
       0     .08       0   156.4    .045       0   175.8      .1       0
Bank Sta=156.4,175.8
XS Rating Curve= 0 ,0
Exp/Cntr=0.3,0.1

Type RM Length L Ch R = 1 ,3608.7  ,357.5,357.3,356.4
XS GIS Cut Line= 3
     1672158.712      607013.582     1672275.032      607003.166
     1672464.268      606900.735
#Sta/Elev= 30
       0  978.47   104.9  975.58   124.8  975.56   126.8  975.37   134.7  972.94
   138.7   972.4   160.1  971.88   174.6  970.36   176.6  970.76   178.6  971.63
   190.5  976.42   196.5  977.07   198.5  977.77   206.4  981.72   212.4  986.22
   214.4  987.42   224.4  992.98   234.3  997.85   238.3 1000.26   244.3 1004.41
   250.3 1010.83   256.2 1017.71   266.2 1027.44   270.2 1030.72   278.2 1035.92
   280.2 1036.88   286.1 1038.47     312  1047.6     324 1051.19     332 1053.13
#Mann= 3 , 0 , 0
       0      .1       0   160.1    .045       0   178.6     .08       0
Bank Sta=160.1,178.6
XS Rating Curve= 0 ,0
Exp/Cntr=0.3,0.1

Type RM Length L Ch R = 1 ,3251.4  ,356.9,357.8,352.6
XS GIS Cut Line= 4
     1672252.462      607414.624     1672363.573      607341.707
     1672518.087      607254.902      1672623.99      607183.721
#Sta/Elev= 30
       0  997.98     9.9  996.07    15.9  994.16    45.6  981.54    57.5   975.8
    67.4  973.82    91.2  970.43   109.1  970.11     115  968.64   130.9  970.75
   166.8  969.45   226.5  968.97   248.4  970.37   258.4  968.64   274.3  968.53
   280.3  967.67   286.2  966.94   296.2  967.01   300.2  967.65   302.2  968.38
   304.2  969.88   308.1  973.59   326.1  987.89     334  993.09     344 1002.06
     356 1008.98     366 1016.22   375.9 1021.18   401.8 1031.55   437.7  1042.7
#Mann= 3 , 0 , 0
       0     .07       0   280.3    .045       0   300.2      .1       0
Bank Sta=280.3,300.2
XS Rating Curve= 0 ,0
Exp/Cntr=0.3,0.1

Type RM Length L Ch R = 1 ,2893.5  ,44.5,46,49.1
XS GIS Cut Line= 3
     1672380.934       607626.43     1672424.337      607600.388
     1672620.518      607480.596
#Sta/Elev= 30
       0  988.14     3.9  986.89    11.7   985.5    13.6  984.58    17.5  980.98
    21.4  978.09    29.2  978.66    38.9  978.56    44.8   978.2    48.7  977.12
    50.6   975.7    58.6  967.66    60.6     966    62.6  964.58    66.6  963.14
    72.6  962.27    80.6  963.02   104.6  964.34   114.6  966.19   126.6  966.58
   144.6  969.03   156.6  969.24   174.5  968.94   200.5   969.3   216.5  969.94
   236.5  971.37   250.5  973.33   258.5  975.73   274.5  982.52   280.5  985.67
#Mann= 3 , 0 , 0
       0      .1       0    66.6    .045       0    80.6      .1       0
Bank Sta=66.6,80.6
XS Rating Curve= 0 ,0
Exp/Cntr=0.3,0.1

Type RM Length L Ch R = 1 ,2847.6  ,45.2,45.2,45.1
XS GIS Cut Line= 2
     1672387.879      607669.832     1672603.157      607551.777
#Sta/Elev= 30
       0  991.81      18  985.35      24  983.78    39.9  978.96    45.9  975.79
    47.9  975.12    49.9  974.87    53.9  975.14    59.9   974.9    73.9  973.33
    75.8   972.9    77.8  972.03    87.8   966.2    93.8  963.04    95.8  962.64
   100.4  963.14   103.8  963.52   109.8  963.35   117.8  964.29   125.8  967.56
   127.8  967.94   135.7  968.27   159.7  967.22   171.7  967.11   203.6  969.05
   211.6  969.87   221.6   971.3   229.6  972.76   237.5  974.74   245.5  975.55
#Mann= 3 , 0 , 0
       0      .1       0    87.8    .045       0   100.4      .1       0
Bank Sta=87.8,100.4
XS Rating Curve= 0 ,0
Exp/Cntr=0.3,0.1

Type RM Length L Ch R = 1 ,2802.4  ,146.8,143.1,138.2
XS GIS Cut Line= 2
     1672417.393      607704.555     1672632.671      607586.499
#Sta/Elev= 30
       0  991.48      14  985.74    43.9  976.78    45.9  975.71    49.9  972.43
    51.9  971.68    65.9   971.4    69.9  970.79    73.9  969.02    75.8  967.82
    77.8   966.3    81.8  962.35    83.8  961.55    85.8  961.53    93.8   961.8
    97.7  962.27   107.8  963.31   115.8  964.89   121.8  965.71   129.8   968.3
   135.7  969.46   143.7  969.77   155.7  969.64   175.7   968.4   185.6  968.87
   205.6  972.82   221.6  975.61   227.6  977.26   239.5  978.53   245.5  979.96
#Mann= 3 , 0 , 0
       0      .1       0    81.8    .045       0    97.7      .1       0
Bank Sta=81.8,97.7
XS Rating Curve= 0 ,0
Exp/Cntr=0.3,0.1

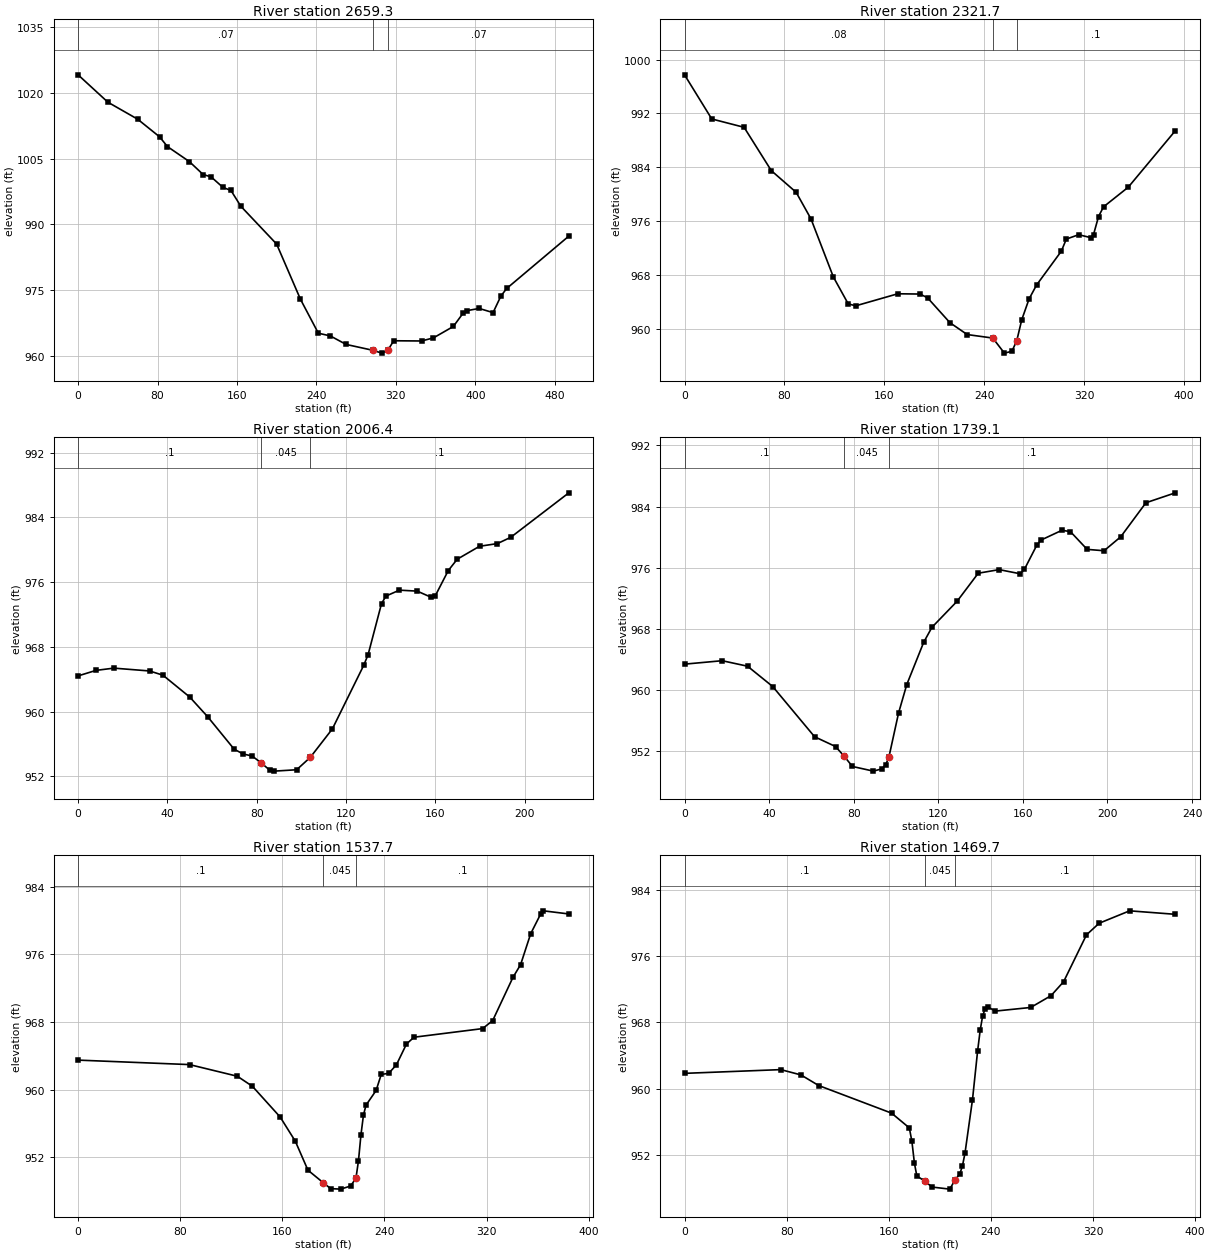
Type RM Length L Ch R = 1 ,2659.3  ,344.7,337.6,325.8
XS GIS Cut Line= 3
     1672362.618      607954.641     1672684.754      607685.457
     1672729.893       607626.43
#Sta/Elev= 30
       0  1024.1      30 1017.86      60 1013.98      82 1009.97      90 1007.73
     112 1004.32   125.9 1001.36   133.9 1000.83   145.9  998.42   153.9  997.73
   163.9  994.12   199.9   985.5   223.9  972.91   241.9  965.17   253.9  964.56
   269.9  962.61   297.1  961.26   305.8  960.63   312.1  961.39   317.8  963.45
   345.8   963.4   357.8  964.11   377.8  966.71   387.8  969.79   391.8  970.33
   403.8  970.82   417.8  969.87   425.7  973.65   431.5  975.37   494.1  987.32
#Mann= 3 , 0 , 0
       0     .07       0   297.1    .045       0   312.1     .07       0
Bank Sta=297.1,312.1
XS Rating Curve= 0 ,0
Exp/Cntr=0.3,0.1

Type RM Length L Ch R = 1 ,2321.7  ,313,315.3,317.5
XS GIS Cut Line= 3
     1672797.514      608080.943     1672809.754      607874.693
     1672900.032      607711.499
#Sta/Elev= 30
       0  997.74    21.8  991.18    47.7  989.94    69.5   983.5    89.4  980.28
   101.3  976.32   119.2   967.7   131.1   963.7   137.1  963.41   170.8   965.2
   188.7  965.16   194.7  964.59   212.6   960.9   226.4  959.14   246.9  958.62
   256.2  956.38   262.2  956.65   266.1  958.22   270.1  961.34     276  964.45
     282  966.51   301.8  971.53   305.8  973.33   315.7  973.98   325.7  973.53
   327.6     974   331.6  976.68   335.6  978.12   355.4  981.04   393.1  989.43
#Mann= 3 , 0 , 0
       0     .08       0   246.9    .045       0   266.1      .1       0
Bank Sta=246.9,266.1
XS Rating Curve= 0 ,0
Exp/Cntr=0.3,0.1

Type RM Length L Ch R = 1 ,2006.4  ,264,267.3,269.8
XS GIS Cut Line= 2
     1673070.171      608015.318     1673200.379      607838.235
#Sta/Elev= 30
       0  964.41       8  965.09      16  965.37      32  965.02      38   964.5
      50   961.8      58  959.38    69.9  955.36    73.9  954.77    77.9  954.52
    81.9   953.7    85.9  952.75    87.9  952.65    97.9  952.82     104  954.35
   113.9  957.87   127.9   965.7   129.9  967.04   135.9  973.34   137.9  974.27
   143.9     975   151.9  974.88   157.9  974.15   159.9  974.26   165.8  977.42
   169.8  978.82   179.8  980.42   187.8  980.75   193.8  981.53   219.8  987.02
#Mann= 3 , 0 , 0
       0      .1       0    81.9    .045       0     104      .1       0
Bank Sta=81.9,104
XS Rating Curve= 0 ,0
Exp/Cntr=0.3,0.1

Type RM Length L Ch R = 1 ,1739.1  ,178.8,201.4,220.7
XS GIS Cut Line= 2
     1673285.448      608154.207     1673445.171      607985.805
#Sta/Elev= 30
       0  963.38    17.8  963.83    29.8  963.11    41.7  960.45    61.5  953.88
    71.4   952.6    75.4  951.36    79.4  949.99    89.3  949.38    93.2  949.67
    95.2  950.24    96.7  951.28   101.2  956.97   105.1  960.71   113.1  966.24
     117   968.2   128.9  971.61   138.9  975.28   148.8  975.75   158.7  975.21
   160.7  975.77   166.6  978.95   168.6  979.62   178.5   980.9   182.5  980.72
   190.4   978.4   198.4  978.22   206.3  980.05   218.2   984.5   232.1   985.8
#Mann= 3 , 0 , 0
       0      .1       0    75.4    .045       0    96.7      .1       0
Bank Sta=75.4,96.7
XS Rating Curve= 0 ,0
Exp/Cntr=0.3,0.1

Type RM Length L Ch R = 1 ,1537.7  ,72.1,67.9,67
XS GIS Cut Line= 5
     1673309.754       608166.36     1673406.976      608206.291
     1673452.115      608209.763     1673564.962      608209.763
     1673670.865      608150.735
#Sta/Elev= 30
       0  963.49    87.3  962.96   124.8  961.58   136.6  960.39   158.3  956.76
   170.2  953.89   180.1  950.46     192  948.99   197.9  948.28   205.8  948.22
   213.5  948.59   217.7  949.51   219.7   951.6   221.6  954.62   223.6     957
   225.6  958.16   233.5   959.9   237.5  961.79   243.4  961.93   249.4  962.93
   257.3   965.4   263.2   966.2   316.9  967.22   324.8  968.16   340.7  973.28
   346.7  974.79   354.6  978.45   362.6  980.84   364.6  981.16   384.5  980.79
#Mann= 3 , 0 , 0
       0      .1       0     192    .045       0   217.7      .1       0
Bank Sta=192,217.7
XS Rating Curve= 0 ,0
Exp/Cntr=0.3,0.1

Type RM Length L Ch R = 1 ,1469.7  ,74.7,64.6,54.4
XS GIS Cut Line= 5
     1673339.268       608228.86      1673436.49      608268.791
     1673481.629      608272.263     1673594.476      608272.263
     1673700.379      608213.235
#Sta/Elev= 30
       0  961.85    75.4   962.3    91.2  961.66   105.1  960.38   162.2  957.05
   176.1  955.27   178.1  953.67   180.1  951.01     182  949.46     188  948.88
   193.9  948.13   207.8  947.88   211.8  948.95   215.7  949.73   217.7  950.67
   219.7   952.2   225.6  958.68   229.6  964.54   231.6  967.03   233.5  968.74
   235.5  969.66   237.5  969.88   243.4  969.36   271.2   969.8   287.1  971.22
     297  972.91   314.9  978.56   324.8  979.96   348.7  981.46   384.5  981.04
#Mann= 3 , 0 , 0
       0      .1       0     188    .045       0   211.8      .1       0
Bank Sta=188,211.8
XS Rating Curve= 0 ,0
Exp/Cntr=0.3,0.1

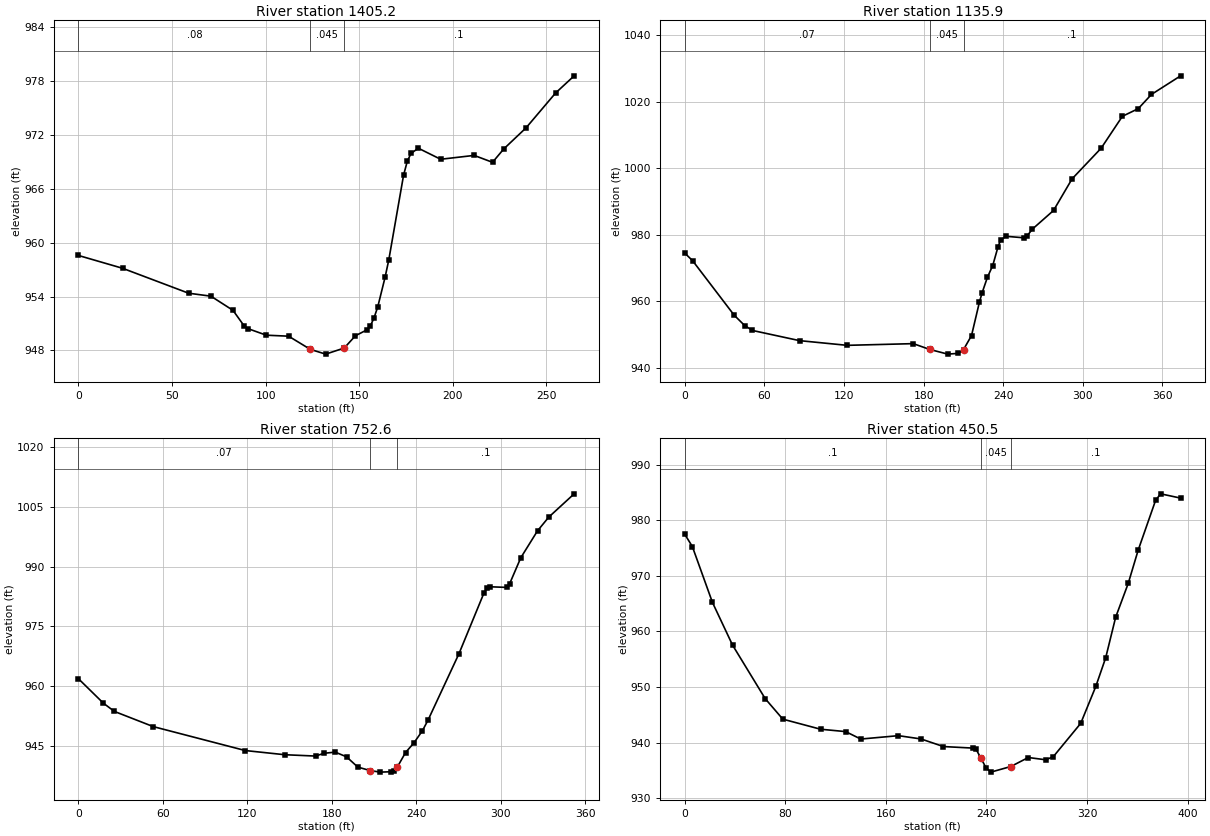
Type RM Length L Ch R = 1 ,1405.2  ,267.2,269.3,270.8
XS GIS Cut Line= 3
     1673424.337      608372.957     1673490.309      608362.541
     1673669.129      608277.471
#Sta/Elev= 30
       0  958.58    23.6  957.15    58.9  954.37    70.8  954.04    82.6  952.46
    88.6  950.71    90.6  950.42   100.4  949.69   112.3  949.58   123.9  948.11
   132.1  947.58     142  948.26     148  949.63   153.9  950.26   155.9   950.7
   157.9  951.61   159.9  952.84   163.8  956.13   165.8  958.08   173.7  967.53
   175.7  969.09   177.7  969.96   181.6  970.53   193.5   969.3   211.4  969.73
   221.2  968.96   227.2  970.45   239.1   972.8   254.9  976.69   264.8   978.6
#Mann= 3 , 0 , 0
       0     .08       0   123.9    .045       0     142      .1       0
Bank Sta=123.9,142
XS Rating Curve= 0 ,0
Exp/Cntr=0.3,0.1

Type RM Length L Ch R = 1 ,1135.9  ,384.2,383.3,381.5
XS GIS Cut Line= 3
     1673486.837      608622.957     1673558.018      608609.068
     1673839.268       608501.43
#Sta/Elev= 30
       0  974.53     5.9  972.24    37.2  955.89    45.1  952.78      51   951.3
    86.5  948.24   122.4  946.83   172.2  947.34   184.5  945.61   198.2  944.19
   206.1  944.42   210.1  945.58   216.1  949.76   222.1  959.89   224.1  962.63
   228.1  967.29   232.1  970.81   236.1  976.46     238  978.41     242  979.58
     256  979.12     258   979.7     262  981.75   277.9  987.33   291.9  996.84
   313.8 1006.04   329.8 1015.62   341.8 1017.93   351.7 1022.19   373.7 1027.78
#Mann= 3 , 0 , 0
       0     .07       0   184.5    .045       0   210.1      .1       0
Bank Sta=184.5,210.1
XS Rating Curve= 0 ,0
Exp/Cntr=0.3,0.1

Type RM Length L Ch R = 1 ,752.6   ,313.8,302.1,290.4
XS GIS Cut Line= 3
      1673592.74      608975.388     1673695.171       608970.18
     1673922.601      608867.749
#Sta/Elev= 30
       0  961.84    17.8  955.66    25.6  953.59    53.2  949.77   118.5  943.75
   146.5   942.7   168.4  942.36   174.4  943.06   182.4  943.35   190.4  942.17
   198.4  939.59   207.2  938.71   214.3  938.32   222.2  938.42   224.3  938.69
   226.3   939.5   232.3  943.25   238.2  945.66   244.2  948.69   248.2  951.36
   270.2  968.09   288.1   983.5   290.1  984.55   292.1  984.95   304.1  984.79
   306.1  985.63   314.1  992.24     326  999.03     334 1002.48     352 1008.33
#Mann= 3 , 0 , 0
       0     .07       0   207.2    .045       0   226.3      .1       0
Bank Sta=207.2,226.3
XS Rating Curve= 0 ,0
Exp/Cntr=0.3,0.1

Type RM Length L Ch R = 1 ,450.5   ,451.9,450.5,447
XS GIS Cut Line= 3
     1673785.448      609305.249     1673943.434      609214.971
     1674068.434      609043.096
#Sta/Elev= 30
       0  977.46       6  975.27      22  965.21      38  957.53      64  947.89
      78  944.21     108   942.4     128  941.97     140  940.63     170  941.24
   187.9  940.65   205.8  939.28   229.6     939   231.6  938.85   235.6  937.19
   239.6  935.49   243.5  934.68   259.4  935.69   273.3  937.31   287.2   936.9
   293.2  937.46     315  943.45     327  950.09   334.9  955.27   342.8  962.54
   352.8  968.63   360.7   974.6   374.6  983.59   378.6  984.75   394.5  983.98
#Mann= 3 , 0 , 0
       0      .1       0   235.6    .045       0   259.4      .1       0
Bank Sta=235.6,259.4
XS Rating Curve= 0 ,0
Exp/Cntr=0.3,0.1

Chan Stop Cuts=-1
Use User Specified Reach Order=0
Composite Channel Slope=5